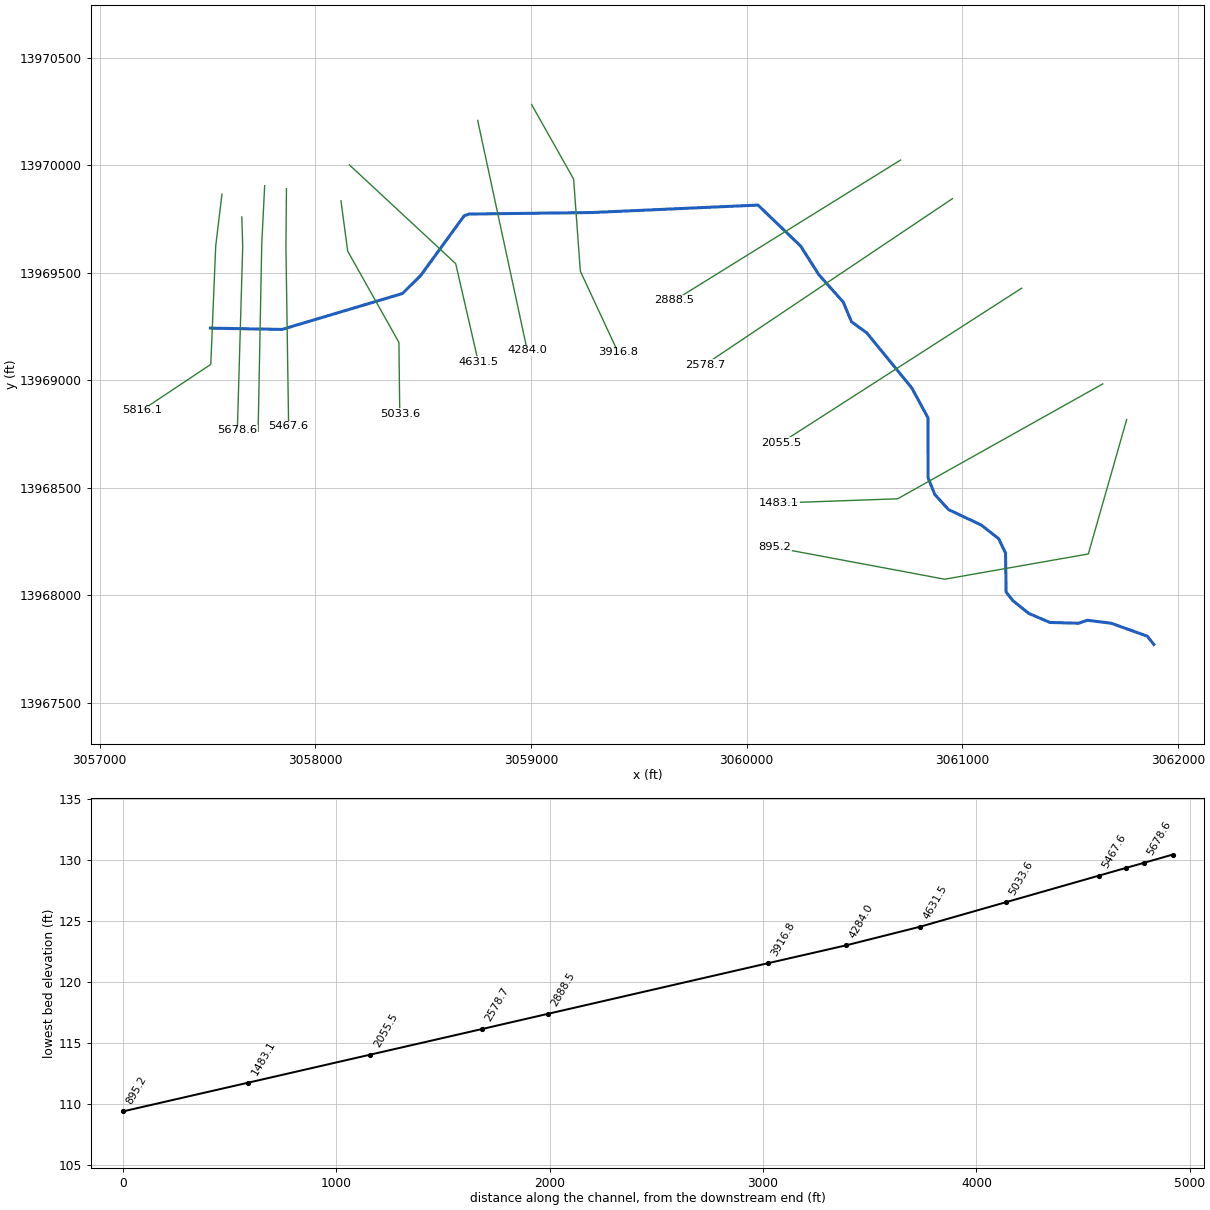
--- M109-00-00.PRJ (project) ---

Proj Title=M109-00-00
Current Plan=p03
Default Exp/Contr=.3,.1
English Units
Geom File=g01
Flow File=f02
Flow File=f03
Plan File=p02
Plan File=p03
Y Axis Title=Elevation
X Axis Title(PF)=Main Channel Distance
X Axis Title(XS)=Station
BEGIN DESCRIPTION:
Willow Creek
Cannon Gully
HCFCD Unit M109-00-00
Flood Hazard Model
10, 2, 1, 0.2% Event
Filename M109-00-00.prj
Prepared by: Halff Associates, Inc. Date: 03/05/2004
Reviewed by:                  Date:
STATUS Final RAS
END DESCRIPTION:
DSS File=dss
DSS Export Rating Curves= 0
DSS Export Rating Curve Sorted= 0
DSS Export Volume Flow Curves= 0
DXF OffsetX= 0
DXF OffsetY= 0
DXF ScaleX= 1
DXF ScaleY= 10

--- M109-00-00.p03 (plan) ---

Plan Title=Floodway
Program Version=3.11
Short Identifier=Floodway0607
Geom File=g01
Flow File=f03
Subcritical Flow
K Sum by GR= 0
Std Step Tol= 0.01
Critical Tol= 0.01
Num of Std Step Trials= 20
Max Error Tol= 0.3
Flow Tol Ratio= 0.001
Split Flow NTrial= 30
Split Flow Tol= 0.02
Split Flow Ratio= 0.02
Log Output Level= 0
Friction Slope Method= 1
Unsteady Friction Slope Method= 2
Unsteady Bridges Friction Slope Method= 1
Parabolic Critical Depth
Global Vel Dist= 0 , 0 , 0
Global Log Level= 0
CheckData=True
Encroach Param=-1 ,0,0, 2
Encroach River=M109-00-00
Encroach Reach=M109-00-00_0009
Encroach Node=5816.1
       1  4968.3  5031.7
Encroach Node=5678.6
       1  4968.9  5032.3
Encroach Node=5637.1
       1  4968.9  5032.3
Encroach Node=5595.6
       1  4968.9  5032.3
Encroach Node=5467.6
       1  4968.3  5031.7
Encroach Node=5033.6
       1  4981.3  5016.9
Encroach Node=4631.5
       1  4973.3  5032.3
Encroach Node=4284.0
       1  4970.5  5029.5
Encroach Node=3916.8
       1    4956    5050
Encroach Node=2888.5
       1 4960.95 5039.05
Encroach Node=2578.7
       1  4952.3  5030.4
Encroach Node=2055.5
       1  4952.3  5030.4
Encroach Node=1483.1
       1  4959.5  5047.7
Encroach Node=895.2
       1  4959.5  5047.7
Computation Interval=1HOUR
Output Interval=1HOUR
Run HTab= 0
Run UNet= 0
Run PostProcess= 0
UNET Theta= 1
UNET Theta Warmup= 1
UNET ZTol= 0.02
UNET ZSATol= 0.1
UNET MxIter= 20
UNET MaxInSteps= 20
UNET DtIC= 0
UNET DtMin= 0
UNET MaxCRTS= 20
UNET WFStab= 2
UNET SFStab= 1
UNET WFX= 1
UNET SFX= 1
UNET DSS MLevel= 4
UNET DZMax Abort= 100
UNET Convert EG Bridges=-1
UNET Use Existing IB Tables=-1
UNET Froude Reduction=False
UNET Froude Limit= 1
UNET Froude Power= 10
Instantaneous Interval=1HOUR
Write IC File= 0
Echo Input=False
Echo Output=False
Write Detailed= 0
Detailed Automatic Start=False, 10

--- M109-00-00.p02 (plan) ---

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Plan Title=FEMA Effective June 2007
Program Version=3.13
Short Identifier=FEMAeff0607
Geom File=g01
Flow File=f02
Encroach Param=-1 ,0,0, 0
DSS File=dss

--- M109-00-00.f03 (steady flow) ---

Flow Title=Floodway
Program Version=3.13
Number of Profiles= 2
Profile Names=1PCT_100yr,1PCTFloodway_100yrFW
River Rch & RM=M109-00-00,M109-00-00_0009       ,5816.1
    1200    1200
River Rch & RM=M109-00-00,M109-00-00_0009       ,4284.0
    1286    1286
River Rch & RM=M109-00-00,M109-00-00_0009       ,2888.5
    2524    2524
Boundary for River Rch & Prof#=M109-00-00,M109-00-00_0009       , 1
Up Type= 0
Dn Type= 3
Dn Slope=0.005
Boundary for River Rch & Prof#=M109-00-00,M109-00-00_0009       , 2
Up Type= 0
Dn Type= 1
Dn Known WS=123.04
DSS Import GetInterval= 0
DSS Import GetPeak= 0
DSS Import FillOption= 0

--- M109-00-00.f02 (steady flow) ---

Flow Title=FEMA Effective June 2007
Program Version=3.13
Number of Profiles= 4
Profile Names=10PCT_10yr, 2PCT_50yr, 1PCT_100yr,0.2PCT_500yr
River Rch & RM=M109-00-00,M109-00-00_0009 ,5816.1
     650    1000    1200    1800
River Rch & RM=M109-00-00,M109-00-00_0009 ,4284.0
     681    1090    1286    1896
River Rch & RM=M109-00-00,M109-00-00_0009 ,2888.5
    1343    2143    2524    3690
Boundary for River Rch & Prof#=M109-00-00,M109-00-00_0009 , 1
Up Type= 0
Dn Type= 3
Dn Slope=0.005
Boundary for River Rch & Prof#=M109-00-00,M109-00-00_0009 , 2
Up Type= 0
Dn Type= 3
Dn Slope=0.005
Boundary for River Rch & Prof#=M109-00-00,M109-00-00_0009 , 3
Up Type= 0
Dn Type= 3
Dn Slope=0.005
Boundary for River Rch & Prof#=M109-00-00,M109-00-00_0009 , 4
Up Type= 0
Dn Type= 3
Dn Slope=0.005
DSS Import GetInterval= 0
DSS Import GetPeak= 0
DSS Import FillOption= 0

--- M109-00-00.g01 (geometry) ---

Geom Title=M109-00-00 June 2007
Program Version=3.13

River Reach=M109-00-00      ,M109-00-00_0009
Reach XY= 30
      3057514.23     13969243.36      3057846.06     13969237.38
       3058404.4      13969404.3      3058489.03     13969488.07
      3058690.86     13969766.28      3058713.86     13969774.09
      3059282.44     13969781.04      3060053.13     13969815.79
       3060250.9     13969625.25      3060335.39     13969492.03
      3060448.36     13969364.82      3060486.97     13969272.73
      3060557.53     13969221.47       3060766.7     13968964.83
      3060841.39     13968826.23      3060842.33     13968546.18
      3060873.35     13968469.28      3060936.63     13968399.35
      3061088.53     13968327.52      3061169.22     13968263.91
      3061201.18     13968197.77      3061203.71     13968015.82
      3061235.67     13967975.31      3061309.09     13967916.14
      3061406.87     13967874.37      3061539.46     13967870.57
       3061580.6     13967884.49      3061691.35     13967870.57
      3061858.44     13967810.45      3061888.82     13967771.84

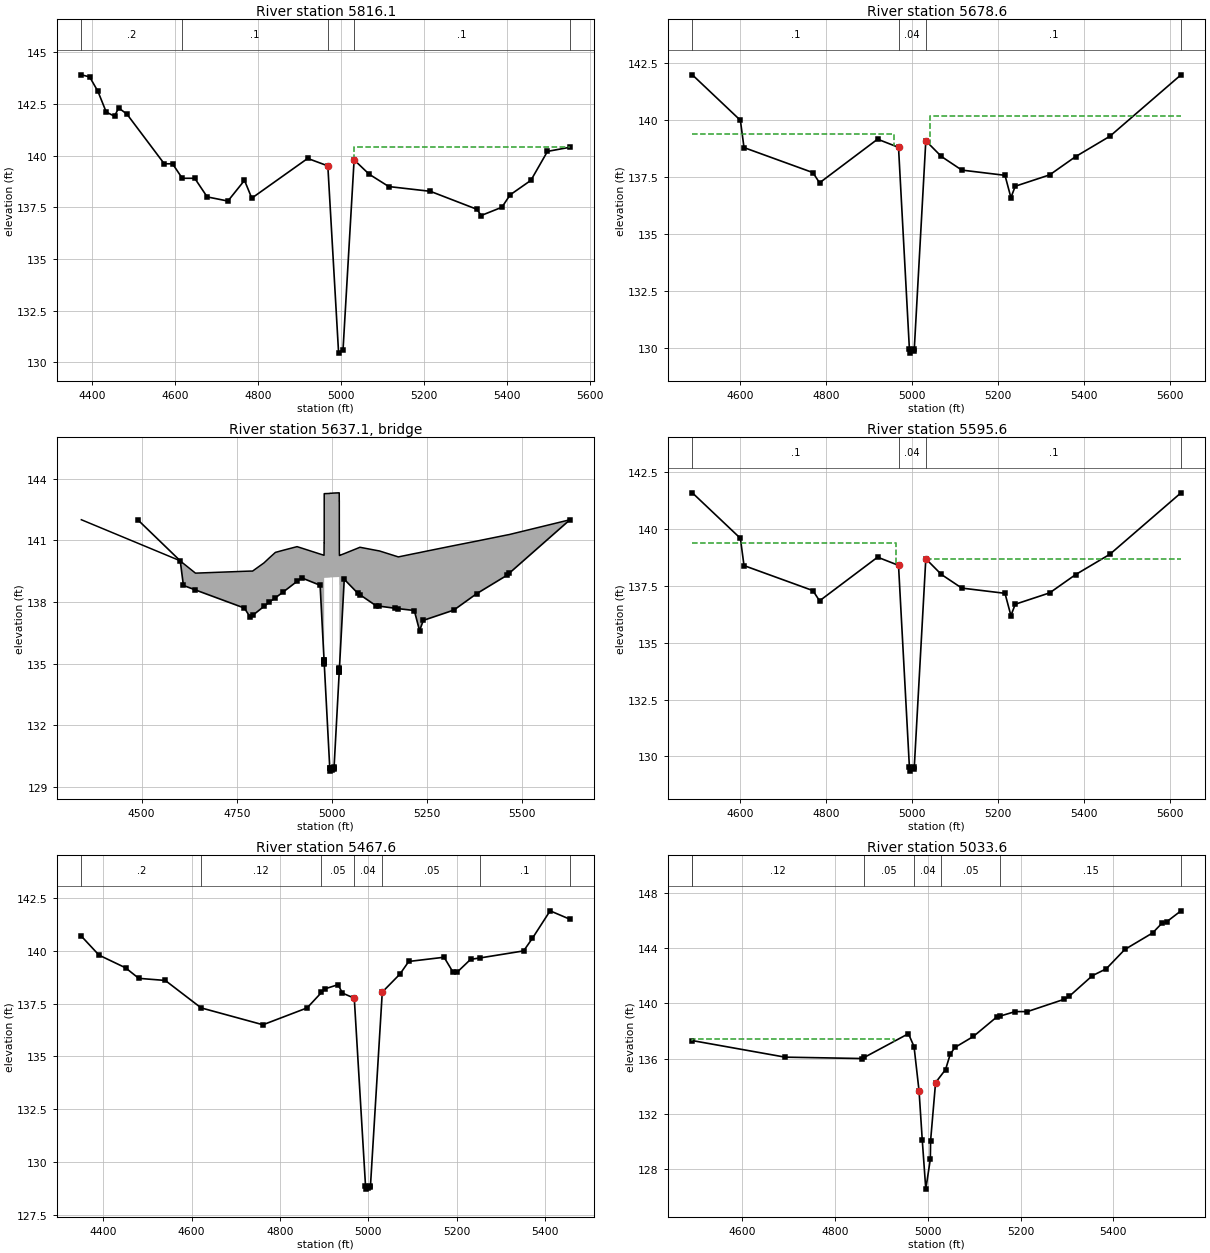
Type RM Length L Ch R = 1 ,5816.1  ,119.35,137.5,123.14
BEGIN DESCRIPTION:
Cross Section 5816.1
Cross Section XS09-Bridge1-con
END DESCRIPTION:
XS GIS Cut Line= 4
      3057567.57      13969866.8      3057538.62       13969625.
      3057515.79      13969074.7      3057196.31      13968861.1
#Sta/Elev= 30
  4373.8   143.9  4393.8   143.8  4413.8   143.1  4433.8   142.1  4453.8   141.9
  4463.8   142.3  4483.8     142  4573.8   139.6  4593.8   139.6  4617.2   138.9
  4647.3   138.9  4677.3     138  4727.3   137.8  4767.3   138.8  4784.9  137.94
  4919.7  139.86  4968.3   139.5  4994.3  130.45    5005  130.62  5031.7  139.79
  5067.8   139.1  5115.3   138.5  5215.6  138.27  5328.1   137.4  5338.1   137.1
  5388.1   137.5  5408.1   138.1  5458.1   138.8  5498.1   140.2  5552.4   140.4
#Mann= 5 ,-1 , 0
  4373.8      .2       0  4617.2      .1       0  4968.3     .04       0
  5031.7      .1       0  5552.4      .2       0
#XS Ineff= 2 , 0
       0  4919.7  139.86  5031.7       0   140.4
Permanent Ineff=
       F       F
Bank Sta=4968.3,5031.7
Exp/Cntr=0.5,0.3

Type RM Length L Ch R = 1 ,5678.6  ,83,83,83
BEGIN DESCRIPTION:
Upstream Section of Bridge/Culvert/Weir
END DESCRIPTION:
XS GIS Cut Line= 3
      3057659.69      13969760.6      3057663.87      13969624.4
      3057638.97      13968768.3
#Sta/Elev= 21
    4490     142  4601.6     140    4610   138.8    4770   137.7  4785.5  137.25
  4920.3  139.17  4968.9  138.81  4994.2  129.93  4994.9  129.76    5005  129.84
  5005.5  129.93  5032.3   139.1  5068.4  138.41  5115.9  137.81  5216.2  137.58
    5230   136.6    5240   137.1    5320   137.6    5380   138.4    5460   139.3
    5625     142
#Mann= 4 ,-1 , 0
    4490      .1       0  4968.9     .04       0  5032.3      .1       0
    5625      .2       0
#XS Ineff= 2 , 0
       0  4958.9   139.4  5042.3       0  140.19
Permanent Ineff=
       F       F
Bank Sta=4968.9,5032.3
Exp/Cntr=0.5,0.3

Type RM Length L Ch R = 3 ,5637.1  ,,,
BEGIN DESCRIPTION:
KUYKENDAHL ROAD
Cross Section 5637.1
Structure ID: M109-00-00-01
END DESCRIPTION:
Bridge Culvert--1,0,-1,-1, 0
Deck Dist Width WeirC Skew NumUp NumDn MinLoCord MaxHiCord MaxSubmerge Is_Ogee
10,63,2.6,0, 51, 51, , , 0.95, 0, 1,1,,
    4342  4601.6    4610  4641.6    4770  4785.5  4791.6  4821.6  4834.8  4851.5
  4871.2  4908.4  4920.3  4968.9  4979.2 4979.31  4979.4 4979.49  4979.6  4979.7
 4979.81  4994.2  4994.3  4994.9    4999    5005  5005.5  5005.6  5019.1 5019.19
  5019.3 5019.41 5019.49  5019.6  5019.7  5032.3  5068.4  5073.4  5115.9  5124.8
  5165.8  5174.3  5216.2    5230    5240    5320    5380    5460  5465.8  5470.1
    5625
     142     140  139.87   139.4  139.49   139.5   139.5   139.9  140.13  140.41
  140.51  140.69  140.62  140.33  140.27   140.6  140.87  140.87  140.87  143.27
  143.27  143.28  143.28  143.29  143.29   143.3   143.3   143.3  143.31  142.93
  142.93  140.53  140.42  140.26  140.26  140.35  140.62  140.66  140.51  140.48
  140.24  140.19  140.35   140.4  140.44  140.74  140.96  141.26  141.28   141.3
     142
     142     140   138.8  138.58   137.7  137.25  137.34  137.78  137.98   138.2
  138.47     139  139.17  138.81  135.19  135.16  135.12  135.09  139.17  139.17
  139.17  139.18  139.18  139.19  139.19   139.2   139.2   139.2  139.21  138.83
  138.83  138.83  138.72  134.75  134.79   139.1  138.41  138.35  137.81  137.79
  137.69  137.67  137.58   136.6   137.1   137.6   138.4   139.3   139.4  139.15
     142
    4342  4601.6    4610  4641.6    4770  4785.5  4791.6  4821.6  4834.8  4851.5
  4871.2  4908.4  4920.3  4968.9  4979.2 4979.31  4979.4 4979.49  4979.6  4979.7
 4979.81  4994.2  4994.3  4994.9    4999    5005  5005.5  5005.6  5019.1 5019.19
  5019.3 5019.41 5019.49  5019.6  5019.7  5032.3  5068.4  5073.4  5115.9  5124.8
  5165.8  5174.3  5216.2    5230    5240    5320    5380    5460  5465.8  5470.1
    5625
  141.59     140  139.87   139.4  139.49   139.5   139.5   139.9  140.13  140.41
  140.51  140.69  140.62  140.33  140.27   140.6  140.87  140.87  140.87  143.27
  143.27  143.28  143.28  143.29  143.29   143.3   143.3   143.3  143.31  142.93
  142.93  140.53  140.42  140.26  140.26  140.35  140.62  140.66  140.51  140.48
  140.24  140.19  140.35   140.4  140.44  140.74  140.96  141.26  141.28   141.3
  141.59
                                                                                
                                  135.04  135.01  134.97  134.94  139.02  139.02
  139.02  139.03  139.03  139.04  139.04  139.05  139.05  139.05  139.06  138.68
  138.68  138.68  138.57   134.6  134.64
                                                                                
        
Abutment Skew #Up #Dn= , 2 , 2
  4979.4  4994.3
  139.17  129.91
  4979.4  4994.3
  139.02  129.76
Abutment Skew #Up #Dn= , 2 , 2
  5005.6 5019.69
  129.96  138.72
  5005.6 5019.69
  129.81  138.57
BR Coef= 1 , 1 , 0 ,1.25, 0 ,,,0.8,0,2,0,
WSPro=,,,, 1 ,,,, 0 ,,,, 0 ,,,,-1 ,-1 ,-1 , 0 , 0 , 0 , 0 , 0
BR U #Sta/Elev= 50
    4490     142  4601.6     140    4610   138.8  4641.6  138.58    4770   137.7
  4785.5  137.25  4791.6  137.34  4821.6  137.78  4834.8  137.98  4851.5   138.2
  4871.2  138.47  4908.4     139  4920.3  139.17  4968.9  138.81  4979.2  135.19
 4979.31  135.16  4979.4  135.12 4979.49  135.09  4979.6  135.05  4979.7  135.02
 4979.81  134.98  4994.2  129.93  4994.3  129.91  4994.9  129.76    4999  129.82
    5005  129.84  5005.5  129.93  5005.6  129.96  5019.1  134.58 5019.19  134.61
  5019.3  134.65 5019.41  134.69 5019.49  134.72  5019.6  134.75  5019.7  134.79
  5032.3   139.1  5068.4  138.41  5073.4  138.35  5115.9  137.81  5124.8  137.79
  5165.8  137.69  5174.3  137.67  5216.2  137.58    5230   136.6    5240   137.1
    5320   137.6    5380   138.4    5460   139.3  5465.8   139.4    5625     142
BR U #Mann= 3
    4490      .1  4968.9    .035  5032.3      .1
BR D #Sta/Elev= 50
    4490  141.59  4601.6  139.59    4610  138.39  4641.6  138.17    4770  137.29
  4785.5  136.84  4791.6  136.93  4821.6  137.37  4834.8  137.57  4851.5  137.79
  4871.2  138.06  4908.4  138.59  4920.3  138.76  4968.9   138.4  4979.2  134.78
 4979.31  134.75  4979.4  134.71 4979.49  134.68  4979.6  134.64  4979.7  134.61
 4979.81  134.57  4994.2  129.52  4994.3   129.5  4994.9  129.35    4999  129.41
    5005  129.43  5005.5  129.52  5005.6  129.55  5019.1  134.17 5019.19   134.2
  5019.3  134.24 5019.41  134.28 5019.49  134.31  5019.6  134.34  5019.7  134.38
  5032.3  138.69  5068.4     138  5073.4  137.94  5115.9   137.4  5124.8  137.38
  5165.8  137.28  5174.3  137.26  5216.2  137.17    5230  136.19    5240  136.69
    5320  137.19    5380  137.99    5460  138.89  5465.8  138.99    5625  141.59
BR D #Mann= 3
    4490      .1  4968.9    .035  5032.3      .1
BC Design=,, 0 ,, 0 ,,,,,,
BC HTab HWMax=142

Type RM Length L Ch R = 1 ,5595.6  ,128,128,128
BEGIN DESCRIPTION:
Downstream Section of Bridge/Culvert/Weir
END DESCRIPTION:
XS GIS Cut Line= 3
      3057765.65      13969905.5      3057752.01      13969631.8
      3057735.31      13968763.5
#Sta/Elev= 21
    4490  141.59  4601.6  139.59    4610  138.39    4770  137.29  4785.5  136.84
  4920.3  138.76  4968.9   138.4  4994.2  129.52  4994.9  129.35    5005  129.43
  5005.5  129.52  5032.3  138.69  5068.4     138  5115.9   137.4  5216.2  137.17
    5230  136.19    5240  136.69    5320  137.19    5380  137.99    5460  138.89
    5625  141.59
#Mann= 4 ,-1 , 0
    4490      .1       0  4968.9     .04       0  5032.3      .1       0
    5625      .2       0
#XS Ineff= 2 , 0
       0 4962.23   139.4 5038.97       0   138.7
Permanent Ineff=
       F       F
Bank Sta=4968.9,5032.3
Exp/Cntr=0.5,0.3

Type RM Length L Ch R = 1 ,5467.6  ,403.34,434,464.18
BEGIN DESCRIPTION:
Cross Section 5467.6
Cross Section XS08-Bridge1-exp
END DESCRIPTION:
XS GIS Cut Line= 3
      3057866.69      13969891.9      3057864.24      13969620.9
      3057876.76      13968785.9
#Sta/Elev= 30
  4350.5   140.7  4390.5   139.8  4450.5   139.2  4480.5   138.7  4540.5   138.6
  4621.6   137.3  4761.6   136.5  4861.6   137.3    4894  138.03  4901.6   138.2
  4931.6   138.4  4941.6     138  4968.3  137.76  4993.7  128.88  4994.3  128.71
  4998.4  128.77  5004.4  128.79    5005  128.88  5031.7  138.05  5071.6   138.9
  5091.6   139.5  5171.6   139.7  5191.6     139  5201.6     139  5231.6   139.6
  5253.7  139.67  5351.6     140  5371.6   140.6  5411.6   141.9  5456.6   141.5
#Mann= 7 ,-1 , 0
  4350.5      .2       0  4621.6     .12       0    4894     .05       0
  4968.3     .04       0  5031.7     .05       0  5253.7      .1       0
  5456.6      .2       0
#XS Ineff= 2 , 0
       0  4919.7  138.12  5031.7       0  138.05
Permanent Ineff=
       F       F
Bank Sta=4968.3,5031.7
Exp/Cntr=0.3,0.1

Type RM Length L Ch R = 1 ,5033.6  ,383.63,402.1,420.9
BEGIN DESCRIPTION:
Cross Section 5033.6
Cross Section xs-07
END DESCRIPTION:
XS GIS Cut Line= 4
      3058119.45      13969835.3      3058150.61      13969601.6
      3058388.19      13969177.1      3058392.08       13968846.
#Sta/Elev= 29
  4492.6   137.3  4692.6   136.1  4858.4     136  4863.1  136.08  4958.4   137.8
  4970.5  136.86  4981.3  133.65  4988.2   130.1  4995.8  126.54  5005.6  128.71
  5006.2  130.06  5016.9  134.26  5038.4   135.2  5048.4   136.3  5058.4   136.8
  5098.4   137.6  5148.4     139  5156.6  139.08  5188.4   139.4  5214.8   139.4
  5294.8   140.3  5304.8   140.5  5354.8     142  5384.8   142.5  5424.8   143.9
  5484.8   145.1  5504.8   145.8  5514.8   145.9  5545.9   146.7
#Mann= 7 , 1 , 0
  4492.6      .2       0  4492.6     .12       0  4863.1     .05       0
  4970.5     .04       0  5029.5     .05       0  5156.6     .15       0
  5545.9      .2       0
#XS Ineff= 2 , 0
       0  4926.3  137.42               0
Permanent Ineff=
       F       F
Bank Sta=4981.3,5016.9
Exp/Cntr=0.3,0.1

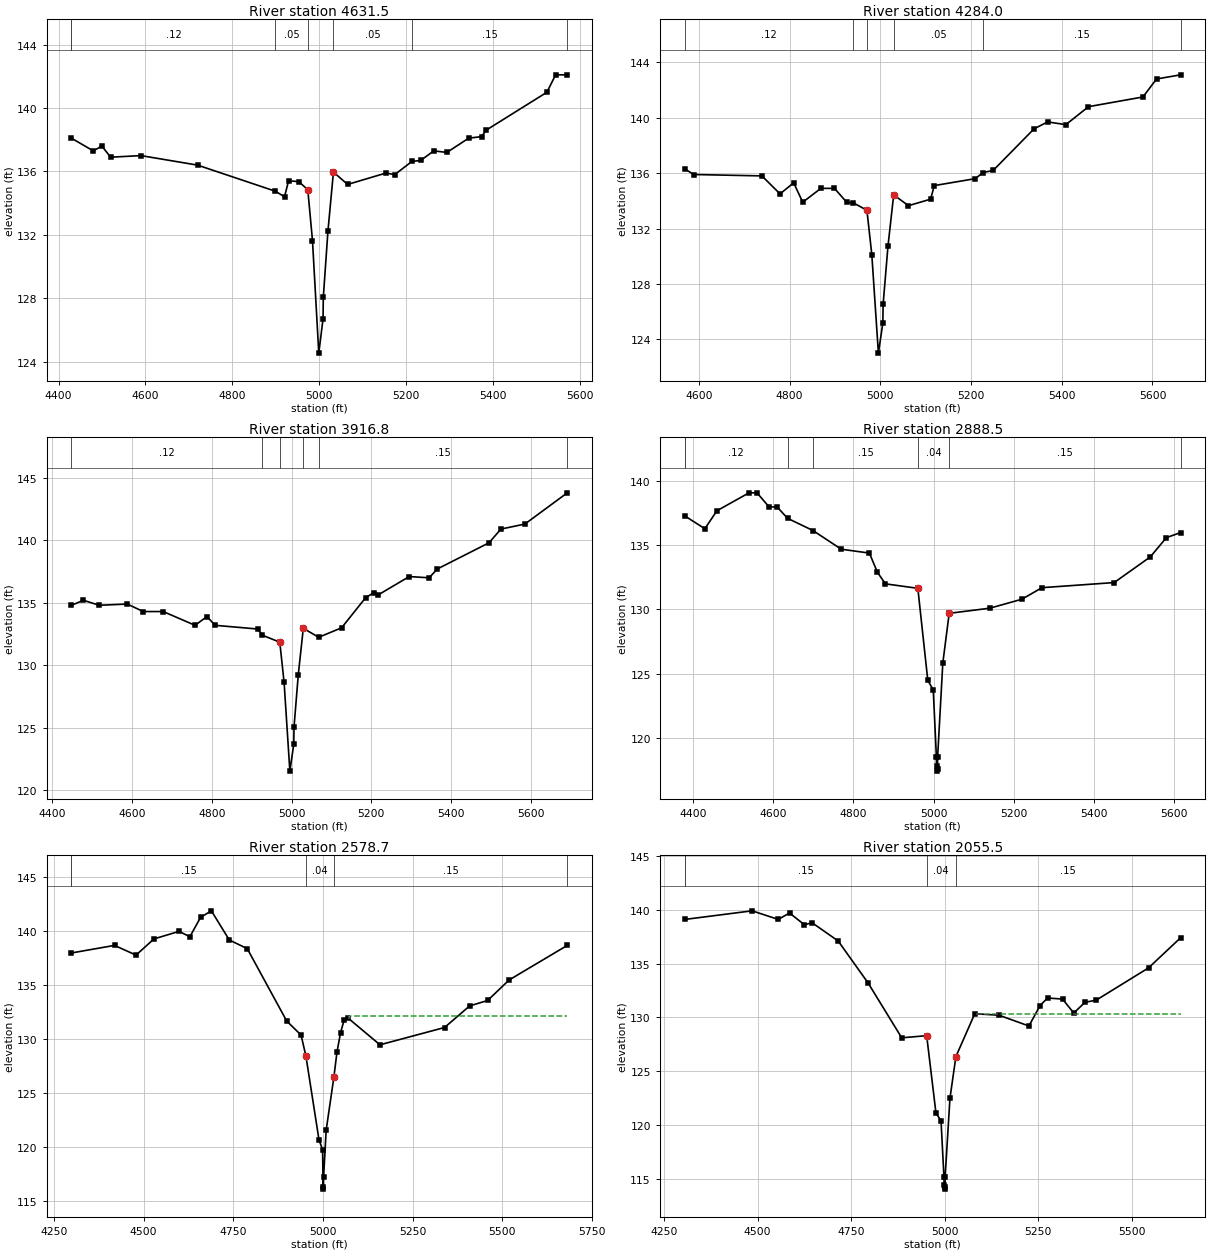
Type RM Length L Ch R = 1 ,4631.5  ,371.05,347.5,283.32
BEGIN DESCRIPTION:
Cross Section 4631.5
Cross Section XS06
END DESCRIPTION:
XS GIS Cut Line= 3
       3058158.9      13970002.4      3058651.51      13969543.2
      3058755.87      13969088.1
#Sta/Elev= 30
  4429.8   138.1  4479.8   137.3  4499.8   137.6  4519.8   136.9  4589.8     137
  4719.8   136.4  4898.9  134.75  4919.8   134.4  4929.1  135.41  4952.4  135.36
  4973.3  134.85  4984.1  131.64  4998.6  124.53  5008.4   126.7    5009  128.05
  5019.7  132.25  5032.3  135.96  5064.9  135.18  5153.2   135.9  5173.2   135.8
  5212.8  136.63  5233.2   136.7  5263.2   137.3  5293.2   137.2  5343.2   138.1
  5373.2   138.2  5383.2   138.6  5523.2     141  5543.2   142.1  5570.1   142.1
#Mann= 7 , 1 , 0
  4429.8      .2       0  4429.8     .12       0  4898.9     .05       0
  4973.3     .04       0  5032.3     .05       0  5212.8     .15       0
  5570.1      .2       0
Bank Sta=4973.3,5032.3
Exp/Cntr=0.3,0.1

Type RM Length L Ch R = 1 ,4284.0  ,371.6,367.2,353.37
BEGIN DESCRIPTION:
Cross Section 4284.0
Cross Section XS05
END DESCRIPTION:
XS GIS Cut Line= 2
      3058753.43      13970209.5      3058983.03      13969140.8
#Sta/Elev= 30
    4569   136.3    4589   135.9    4739   135.8    4779   134.5    4809   135.3
    4829   133.9    4869   134.9    4899   134.9  4926.3  133.88  4940.8  133.85
  4970.5  133.32  4981.3  130.11  4995.8     123  5005.6  125.17  5006.2  126.52
  5016.9  130.72  5029.5  134.43  5062.1  133.65    5111  134.12    5119   135.1
    5209   135.6  5226.8  136.04    5249   136.2    5339   139.2    5369   139.7
    5409   139.5    5459   140.8    5579   141.5    5609   142.8  5662.1   143.1
#Mann= 6 ,-1 , 0
    4569     .12       0  4940.8     .05       0  4970.5     .04       0
  5029.5     .05       0  5226.8     .15       0  5662.1      .2       0
#XS Ineff= 2 , 0
       0    4899   134.9  5029.5       0  134.43
Permanent Ineff=
       F       F
Bank Sta=4970.5,5029.5
Exp/Cntr=0.3,0.1

Type RM Length L Ch R = 1 ,3916.8  ,1066.87,1028.3,972.03
BEGIN DESCRIPTION:
Cross Section 3916.8
Cross Section xs-04
END DESCRIPTION:
XS GIS Cut Line= 4
      3059003.57      13970283.2      3059198.31      13969936.6
      3059229.47      13969508.1      3059404.73      13969130.3
#Sta/Elev= 30
    4448   134.8    4478   135.2    4518   134.8    4588   134.9    4628   134.3
    4678   134.3    4758   133.2    4788   133.9    4808   133.2  4915.6   132.9
  4926.5  132.41  4970.5  131.85  4981.3  128.64  4995.8  121.53  5005.6   123.7
  5006.2  125.05  5016.9  129.25  5029.5  132.96  5068.1  132.24  5125.6     133
  5185.6   135.4  5205.6   135.8  5215.6   135.6  5295.2   137.1  5345.2     137
  5365.2   137.7  5495.2   139.8  5525.2   140.9  5585.2   141.3  5691.6   143.8
#Mann= 6 ,-1 , 0
    4448     .12       0  4926.5     .05       0  4970.5     .04       0
  5029.5     .05       0  5068.1     .15       0  5691.6      .2       0
Bank Sta=4970.5,5029.5
Exp/Cntr=0.3,0.1

Type RM Length L Ch R = 1 ,2888.5  ,305.97,309.8,307.45
BEGIN DESCRIPTION:
Cross Section 2888.5
Cross Section XS03
END DESCRIPTION:
XS GIS Cut Line= 2
      3060714.54      13970025.3      3059665.56      13969372.4
#Sta/Elev= 30
  4380.2   137.3  4430.2   136.3  4460.2   137.7  4540.2   139.1  4560.2   139.1
  4590.2     138  4610.2     138  4636.4  137.11  4699.5  136.16  4770.2   134.7
  4840.2   134.4  4860.2   132.9  4880.2     132 4960.95  131.65 4985.75  124.47
 4999.35  123.73 5007.15  118.52 5007.45  117.76 5008.95  117.39 5009.95  117.59
 5010.25  118.48 5023.15  125.82 5039.05   129.7  5140.2   130.1  5220.2   130.8
  5270.2   131.7  5450.2   132.1  5540.2   134.1  5580.2   135.6  5615.8     136
#Mann= 7 , 1 , 0
  4380.2      .2       0  4380.2     .12       0  4636.4     .05       0
  4699.5     .15       0 4960.95     .04       0 5039.05     .15       0
  5615.8      .2       0
Bank Sta=4960.95,5039.05
Exp/Cntr=0.3,0.1

Type RM Length L Ch R = 1 ,2578.7  ,514.12,523.2,513.09
BEGIN DESCRIPTION:
Cross Section XS2.5
END DESCRIPTION:
XS GIS Cut Line= 2
      3060954.89      13969845.6      3059808.16      13969074.1
#Sta/Elev= 30
  4298.8     138  4418.8   138.7  4478.8   137.8  4528.8   139.3  4598.8     140
  4628.8   139.5  4658.8   141.3  4688.8   141.9  4738.8   139.2  4788.8   138.4
  4898.8   131.7  4938.8   130.4  4952.3  128.47  4988.8   120.7  4998.8   119.8
  5000.3  116.14  5001.3  116.34  5001.6  117.23  5008.8   121.6  5030.4  126.53
  5038.8   128.8  5048.8   130.6  5058.8   131.8  5068.8     132  5158.8   129.5
  5338.8   131.1  5408.8   133.1  5458.8   133.6  5518.8   135.5  5680.9   138.7
#Mann= 5 , 1 , 0
  4298.8      .2       0  4298.8     .15       0  4952.3     .04       0
  5030.4     .15       0  5680.9      .2       0
#XS Ineff= 2 , 0
                         5071.79          132.21
Permanent Ineff=
       F       F
Bank Sta=4952.3,5030.4
Exp/Cntr=0.3,0.1

Type RM Length L Ch R = 1 ,2055.5  ,570.62,572.4,553.69
BEGIN DESCRIPTION:
Cross Section 2055.5
Cross Section XS02
END DESCRIPTION:
XS GIS Cut Line= 2
      3061276.02       13969429.      3060161.76      13968710.8
#Sta/Elev= 30
  4305.6   139.1  4485.6   139.9  4555.6   139.1  4585.6   139.7  4625.6   138.6
  4645.6   138.8  4715.6   137.1  4795.6   133.2  4885.6   128.1  4952.3   128.3
  4977.1  121.12  4990.7  120.38  4998.5  115.17  4998.8  114.41  5000.3  114.04
  5001.3  114.24  5001.6  115.13  5014.5  122.47  5030.4  126.35  5080.9  130.34
  5145.6   130.2  5225.6   129.2  5255.6   131.1  5275.6   131.8  5315.6   131.7
  5345.6   130.4  5375.6   131.4  5405.6   131.6  5545.6   134.6  5631.3   137.4
#Mann= 4 , 1 , 0
  4305.6      .2       0  4305.6     .15       0  4952.3     .04       0
  5030.4     .15       0
#XS Ineff= 2 , 0
                         5085.47          130.34
Permanent Ineff=
       F       F
Bank Sta=4952.3,5030.4
Exp/Cntr=0.3,0.1

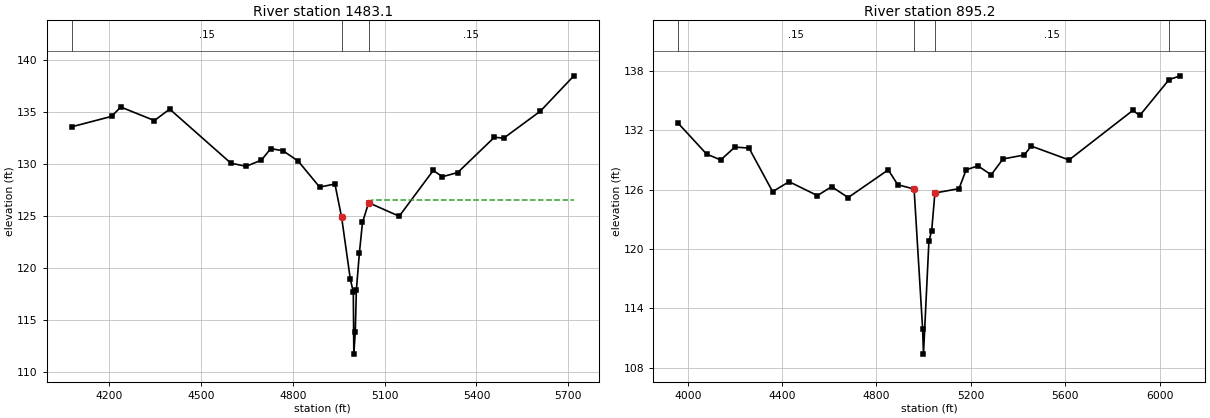
Type RM Length L Ch R = 1 ,1483.1  ,598.86,587.9,544.33
BEGIN DESCRIPTION:
Cross Section XS1.5
END DESCRIPTION:
XS GIS Cut Line= 3
      3061651.96       13968984.      3060700.67      13968449.5
      3060151.48      13968429.9
#Sta/Elev= 30
  4077.6   133.6  4207.6   134.6  4237.6   135.5  4347.6   134.2  4397.6   135.3
  4597.6   130.1  4647.6   129.8  4697.6   130.4  4727.6   131.5  4767.6   131.3
  4817.6   130.3  4887.6   127.8  4937.6   128.1  4959.5  124.88  4987.6     119
  4997.6   117.7  4999.3  111.74    5004  113.86  5007.6   117.9  5017.6   121.5
  5027.6   124.4  5047.7   126.3  5147.6     125  5258.8   129.4  5288.8   128.8
  5338.8   129.2  5458.8   132.6  5488.8   132.5  5608.8   135.1  5718.3   138.5
#Mann= 3 ,-1 , 0
  4077.6     .15       0  4959.5     .04       0  5047.7     .15       0
#XS Ineff= 2 , 0
                         5057.69          126.56
Permanent Ineff=
       F       F
Bank Sta=4959.5,5047.7
Exp/Cntr=0.3,0.1

Type RM Length L Ch R = 1 ,895.2   ,0,0,0
BEGIN DESCRIPTION:
Cross Section 895.2
Cross Section XS01
END DESCRIPTION:
XS GIS Cut Line= 4
      3061762.89      13968818.3      3061585.05      13968192.9
      3060919.11      13968075.4      3060131.29      13968223.4
#Sta/Elev= 30
  3959.8   132.7  4079.8   129.6  4139.8     129  4199.8   130.3  4259.8   130.2
  4359.8   125.8  4429.8   126.8  4549.8   125.4    4610   126.3    4680   125.2
    4850     128    4890   126.5  4959.5  126.06  4995.6  111.96  4999.3  109.38
  5022.4  120.81  5034.1  121.86  5047.7  125.66    5150   126.1    5180     128
    5230   128.4  5286.3   127.5  5336.3   129.1  5426.3   129.5  5456.3   130.4
  5616.3     129  5886.3     134  5916.3   133.5  6040.3  137.12  6087.9   137.5
#Mann= 4 ,-1 , 0
  3959.8     .15       0  4959.5     .04       0  5047.7     .15       0
  6040.3      .2       0
Bank Sta=4959.5,5047.7
Exp/Cntr=0.3,0.1

Chan Stop Cuts=-1
Use User Specified Reach Order=0
User Specified Reach Order=M109-00-00      ,Reach - 1